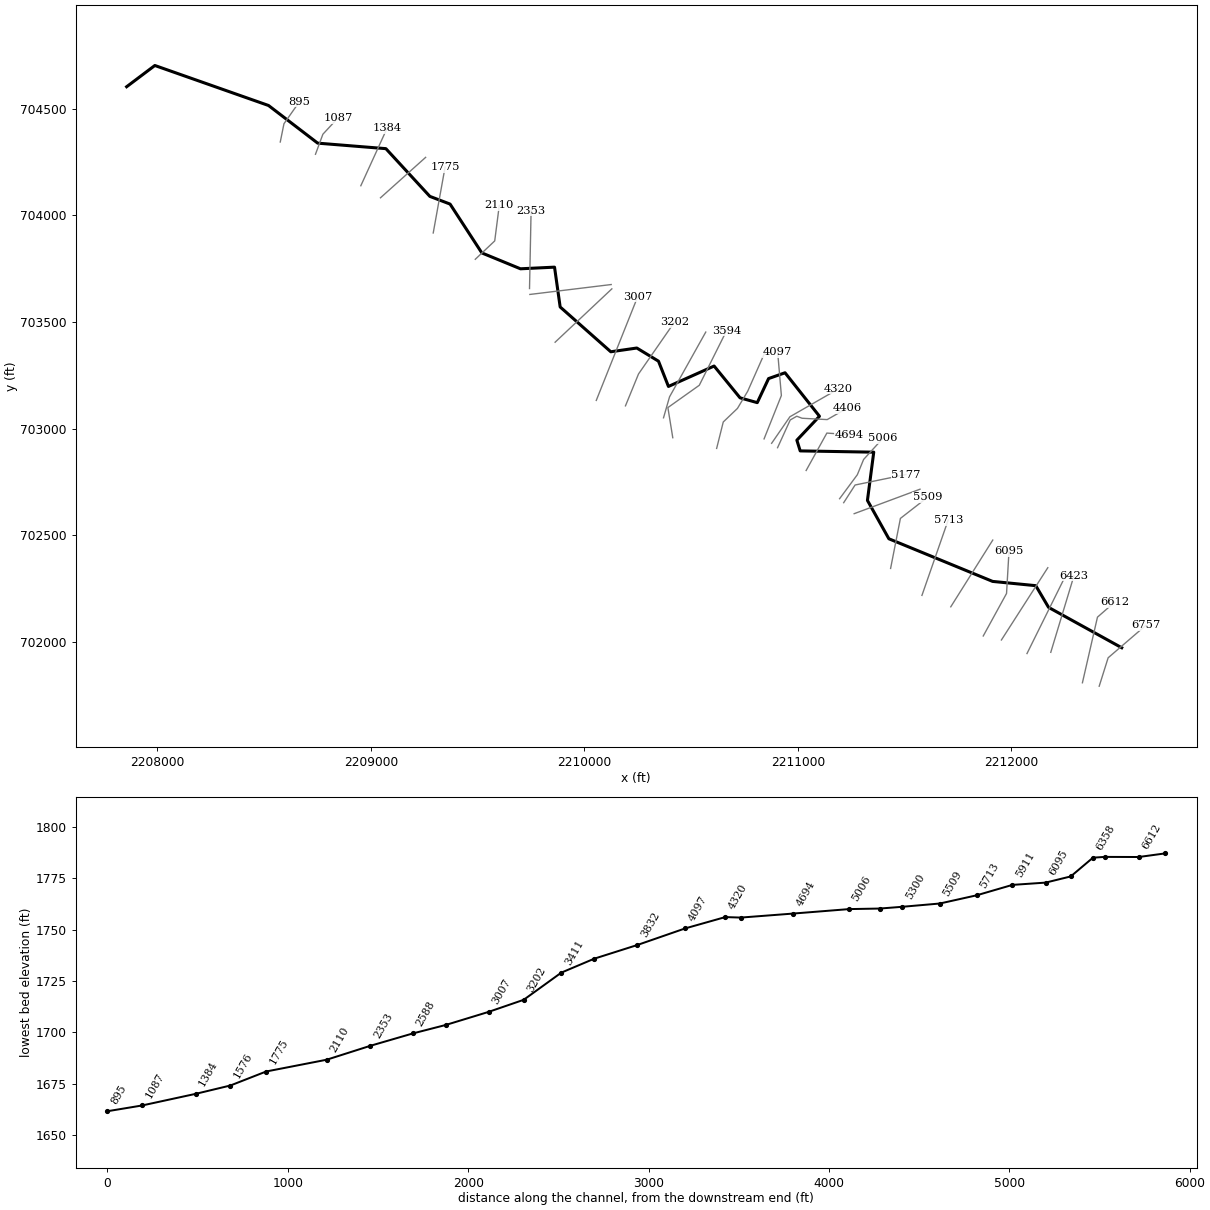
--- SANDRNT1.prj (project) ---

Proj Title=SANDRNT1
Current Plan=p01
Default Exp/Contr=0.3,0.1
English Units
Geom File=g01
Flow File=f01
Plan File=p01
Y Axis Title=Elevation
X Axis Title(PF)=Main Channel Distance
X Axis Title(XS)=Station
BEGIN DESCRIPTION:
---------- MODELED AS PART OF WVEMD CTP PROGRAM, 2023----------
Stream Name: Sand Run Tributary 1
Flood Zone:  AFH
Upshur County, WV
HEC-RAS Version: RAS 6.3
Vertical Datum: NAVD88
Projection: NAD 1983 StatePlane West Virginia S FIPS 4702 (US Feet)
Terrain: 1-meter LIDAR (FEMA Region III 3DEP collected 2016-2018)
Land Use: 2019 NLCD
Hydrologic Method:
WV 2010 Regional Regression Equations
Additional Model Notes:
Main stem is SANDRN1; main stem model is not finished yet, so tie-in hasn't been checked
END DESCRIPTION:
DSS Export Rating Curves= 0
DSS Export Rating Curve Sorted= 0
DSS Export Volume Flow Curves= 0
DXF OffsetX= 0
DXF OffsetY= 0
DXF ScaleX= 1
DXF ScaleY= 10

--- SANDRNT1.p01 (plan) ---

Plan Title=Floodplain
Program Version=4.10
Short Identifier=Floodplain
Geom File=g01
Flow File=f01
Subcritical Flow
K Sum by GR= 0
Std Step Tol= 0.01
Critical Tol= 0.01
Num of Std Step Trials= 20
Max Error Tol= 0.3
Flow Tol Ratio= 0.001
Split Flow NTrial= 30
Split Flow Tol= 0.02
Split Flow Ratio= 0.02
Log Output Level= 0
Friction Slope Method= 1
Unsteady Friction Slope Method= 2
Unsteady Bridges Friction Slope Method= 1
Parabolic Critical Depth
Global Vel Dist= 0 , 0 , 0
Global Log Level= 0
CheckData=True
Encroach Param=-1 ,0,0, 0
Computation Interval=1MIN
Output Interval=1HOUR
Run HTab= 0
Run UNet= 0
Run PostProcess= 0
Run WQNet= 0
UNET Theta= 1
UNET Theta Warmup= 1
UNET ZTol= 0.02
UNET ZSATol= 0.02
UNET MxIter= 20
UNET MaxInSteps= 0
UNET DtIC= 0
UNET DtMin= 0
UNET MaxCRTS= 20
UNET WFStab= 2
UNET SFStab= 1
UNET WFX= 1
UNET SFX= 1
UNET DSS MLevel= 4
UNET DZMax Abort= 100
UNET Convert EG Bridges= 0
UNET Use Existing IB Tables=-1
UNET Froude Reduction=False
UNET Froude Limit= 0.8
UNET Froude Power= 4
UNET Time Slicing=0,0, 5
UNET Junction Losses=0
Instantaneous Interval=1HOUR
Write IC File= 0
Write IC File at Sim End=0
Echo Input=False
Echo Parameters=False
Echo Output=False
Write Detailed= 0
WQ AD Non Conservative
WQ ULTIMATE=-1
WQ Max Comp Step=1HOUR
WQ Output Interval=15MIN
WQ Output Selected Increments= 0
WQ Output face flow=0
WQ Output face velocity=0
WQ Output face area=0
WQ Output face dispersion=0
WQ Output cell volume=0
WQ Output cell surface area=0
WQ Output cell continuity=0
WQ Output cumulative cell continuity=0
WQ Output face conc=0
WQ Output face dconc_dx=0
WQ Output face courant=0
WQ Output face peclet=0
WQ Output face adv mass=0
WQ Output face disp mass=0
WQ Output cell mass=0
WQ Output cell source sink temp=0
WQ Output cell source sink nsm=0
WQ Output MaxMinRange=-1
WQ Daily Max Min Mean=-1
WQ Daily Range=0
WQ Daily Time=0
WQ Create Restart=0
WQ Fixed Restart=0
WQ System Summary=0
WQ Use Fixed Temperature=0
Sorting and Armoring Iterations= 10
XS Update Threshold= 0.02
Hydraulics Update Threshold= 0.02
Energy Slope Method= 1
Volume Change Method= 1
XS Weighting Method= 0
Number of US Weighted Cross Sections= 1
Number of DS Weighted Cross Sections= 1
Upstream XS Weight=0
Main XS Weight=1
Downstream XS Weight=0
Number of DS XS's Weighted with US Boundary= 1
Upstream Boundary Weight= 1
Weight of XSs Associated with US Boundary= 0
Number of US XS's Weighted with DS Boundary= 1
Downstream Boundary Weight= 0.5
Weight of XSs Associated with DS Boundary= 0.5
Sediment Output Level= 3
Mass or Volume Output= 0
Output Increment Type= 1
Profile and TS Output Increment= 1
XS Output Flag= 0
XS Output Increment= 10
Disregard all LS=0
Disregard all Conn=0
Disregard all Breaches=0
Disregard all Pumps=0

--- SANDRNT1.f01 (steady flow) ---

Flow Title=Flows
Program Version=4.10
Number of Profiles= 1
Profile Names=01pct
River Rch & RM=SANDRNT1,Main            ,6757
     357
River Rch & RM=SANDRNT1,Main            ,1775
     615
Boundary for River Rch & Prof#=SANDRNT1,Main            , 1
Up Type= 0
Dn Type= 3
Dn Slope=0.00374
DSS Import GetInterval= 0
DSS Import GetPeak= 0
DSS Import FillOption= 0

--- SANDRNT1.g01 (geometry) ---

Geom Title=Geometry
Program Version=6.31

River Reach=SANDRNT1        ,Main
Reach XY= 30
2212517.29471659701972.3914969432212174.54964301702161.791603833
2212114.62686259702263.5230276732211912.50948468702283.468525842
2211426.37430209702483.4399106652211325.98801993702663.379511416
2211355.54865634702889.5348990112211010.97880742702895.515858173
2210995.38271001 702945.737542512211101.26340376 703057.99978517
2210939.95270276703261.9485242522210862.88888051703234.705796584
2210809.86273985703121.8142900912210729.19328175703144.392657012
2210607.68794735703293.5124375082210393.78056675703197.790844172
2210347.13564692703316.2338487512210245.60468201703377.959447086
2210123.67054267703360.3889441792209886.46924542703570.490558088
2209860.11332701703757.2126255932209700.46272768703749.514806345
  2209519.578575703823.9172165842209370.71601184704052.991561592
2209275.99572884704089.1053345052209070.07225618704312.914270088
2208750.54172726704338.7262263452208520.23706976 704515.31773667
2207987.62855493 704702.898398252207855.44968542704603.255881011

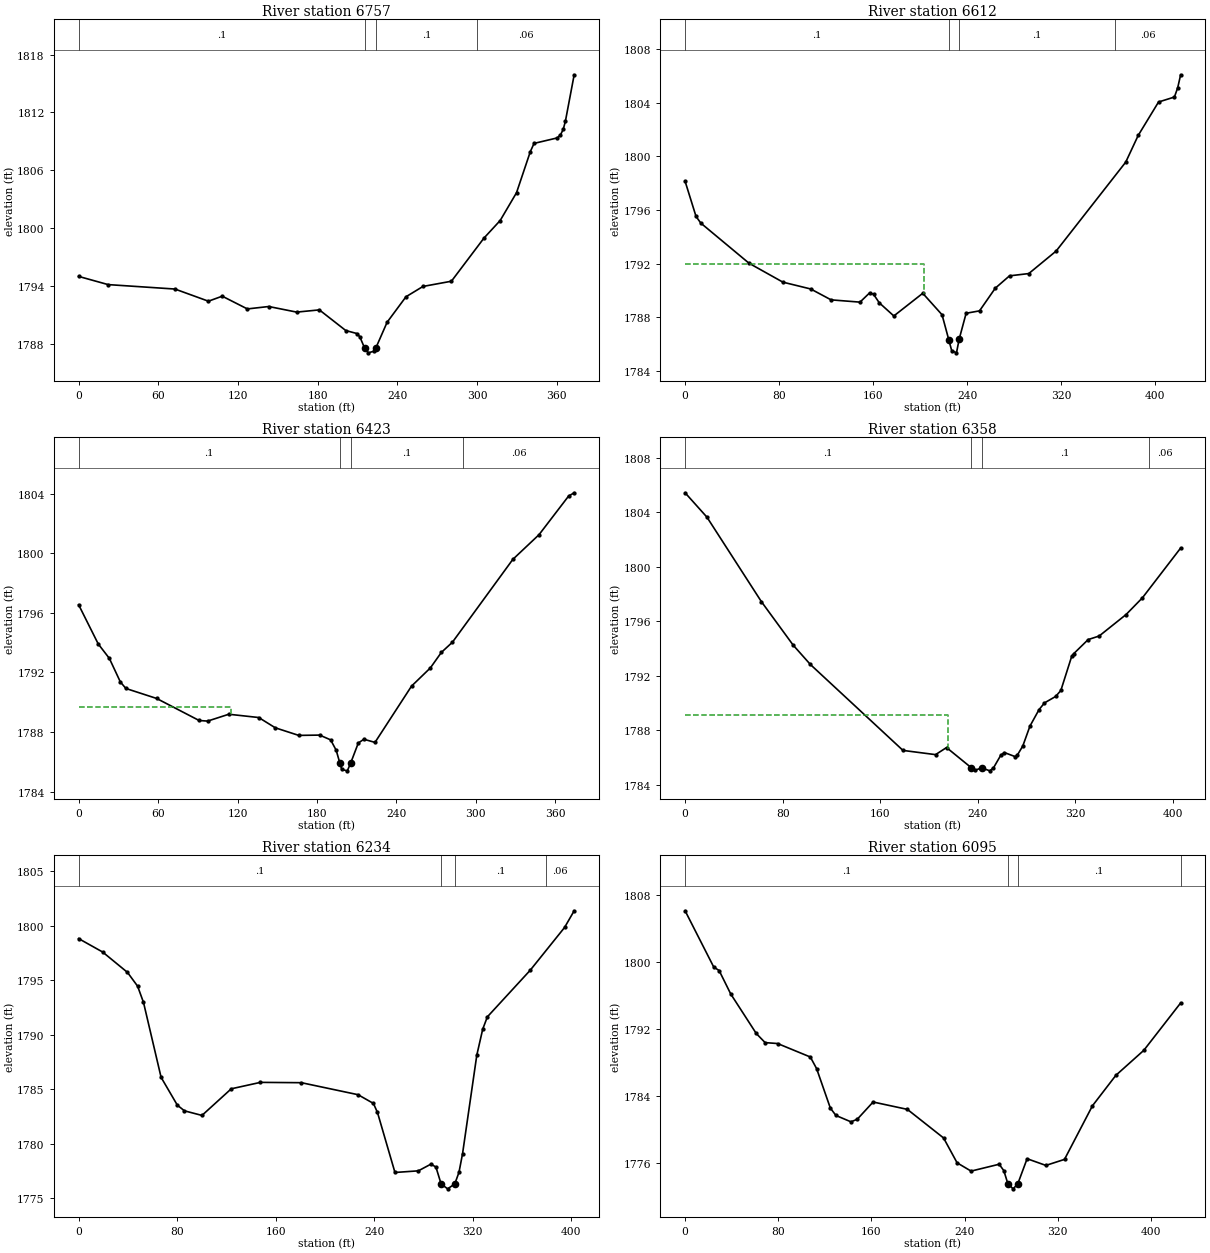
Type RM Length L Ch R = 1 ,6757    ,145.4,145.8,145.4
XS GIS Cut Line= 3
 2212411.7441001701791.9844989412212453.67476402701925.336547409
2212630.41303758702077.466483606
#Sta/Elev= 30
       0 1795.01    22.2 1794.16    72.5  1793.7    97.7 1792.44   108.1 1792.96
     127 1791.64   143.1 1791.89   164.1 1791.31   181.2 1791.54   201.1  1789.4
   209.5 1789.09   211.7 1788.74   215.2  1787.6     218 1787.09   222.3 1787.26
  223.741787.603   232.2 1790.26   246.4  1792.9   259.2 1793.97   280.6 1794.51
   305.1 1798.98   317.3  1800.8   329.6 1803.68     340 1807.94   342.8 1808.79
   360.3 1809.36   362.7 1809.67   364.8 1810.26   366.4 1811.09     373  1815.9
#Mann= 4 ,-1,0
       0      .1       0   215.2    .045       0  223.74      .1       0
  299.79     .06       0
Bank Sta=215.2,223.74
XS Rating Curve= 0 ,0
Exp/Cntr(USF)=0,0
Exp/Cntr=0.3,0.1

Type RM Length L Ch R = 1 ,6612    ,188.3,188.2,186.9
XS GIS Cut Line= 3
2212333.15747211701808.1067123162212403.60531972702115.817593879
2212483.35760004702185.600839158
#Sta/Elev= 30
       0 1798.13     9.3 1795.51    13.4 1795.01    54.4 1792.02    83.2 1790.61
   106.9  1790.1   124.2 1789.29   148.8 1789.12     157 1789.81   160.3 1789.71
   165.2 1789.07   177.6 1788.09   202.2 1789.78   218.6 1788.18  224.281786.333
   226.8 1785.51   230.9 1785.34  233.171786.358   239.1 1788.29   250.5 1788.47
   263.9 1790.16     276 1791.08   292.4 1791.25   315.7 1792.93   374.9 1799.56
   385.5 1801.55   402.8 1804.04   416.3 1804.41   419.1  1805.1   421.6 1806.07
#Mann= 4 ,-1,0
       0      .1       0  224.28    .045       0  233.17      .1       0
  365.67     .06       0
#XS Ineff= 2 , 0
          202.97 1791.99
Permanent Ineff=
       F       F
Bank Sta=224.28,233.17
XS Rating Curve= 0 ,0
Exp/Cntr(USF)=0,0
Exp/Cntr=0.3,0.1

Type RM Length L Ch R = 1 ,6423    ,67.3,65.8,64.2
XS GIS Cut Line= 2
2212184.95115118701950.9962145542212293.28133195702309.216873651
#Sta/Elev= 30
       0 1796.54    14.8 1793.91    23.2 1792.94    31.5 1791.36    35.7 1790.92
    58.9 1790.25      91 1788.77    97.4 1788.73   113.4 1789.19     136 1788.97
   148.5 1788.28   166.2 1787.77     182 1787.79   190.3 1787.47   194.5 1786.77
  197.191785.933   198.7 1785.48   202.9 1785.39  205.461785.921   211.2 1787.26
   215.4 1787.51   223.8  1787.3   251.4 1791.08   265.6  1792.3   273.9 1793.34
   282.3 1794.03   327.9 1799.59   347.7 1801.25     370 1803.84   374.2 1804.06
#Mann= 4 ,-1,0
       0      .1       0  197.19    .045       0  205.46      .1       0
     290     .06       0
#XS Ineff= 2 , 0
          115.33 1789.67
Permanent Ineff=
       F       F
Bank Sta=197.19,205.46
XS Rating Curve= 0 ,0
Exp/Cntr(USF)=0,0
Exp/Cntr=0.3,0.1

Type RM Length L Ch R = 1 ,6358    ,122.9,123.2,122.3
XS GIS Cut Line= 2
2212073.48220023701945.1451447642212253.66327798 702309.19953548
#Sta/Elev= 30
       0 1805.43    17.9 1803.64    62.5 1797.44    88.6 1794.24   102.7 1792.82
   178.6 1786.51   205.3  1786.2   214.3 1786.72  234.741785.229   237.9 1785.06
   243.11785.229   249.8 1785.01   252.8 1785.23   258.8 1786.16   261.8 1786.35
   270.7 1786.05   272.3 1786.16   276.8 1786.83   282.7  1788.3   290.1  1789.5
   294.6    1790   303.7 1790.47     308 1790.91   316.9 1793.42   318.5 1793.61
   330.4 1794.65   339.4 1794.91   361.5 1796.49   374.9 1797.72   406.2 1801.37
#Mann= 4 ,-1,0
       0      .1       0  234.74    .045       0   243.1      .1       0
     380     .06       0
#XS Ineff= 2 , 0
          215.62 1789.14
Permanent Ineff=
       F       F
Bank Sta=234.74,243.1
XS Rating Curve= 0 ,0
Exp/Cntr(USF)=0,0
Exp/Cntr=0.3,0.1

Type RM Length L Ch R = 1 ,6234    ,133,139.1,143.8
XS GIS Cut Line= 2
2211953.66953826702008.8166177852212170.99450213702347.763809139
#Sta/Elev= 30
       0 1798.82    19.5 1797.59    39.7 1795.72    47.9 1794.46    52.7 1792.97
      67  1786.1    80.2 1783.55      86 1783.03   100.2 1782.61     124 1785.05
   147.7 1785.64     181 1785.61     227 1784.51   239.5 1783.71   242.8 1782.88
     257 1777.38     276 1777.53   286.3 1778.15   290.3 1777.87   294.5 1776.33
   299.8 1775.88  305.591776.331     309 1777.39   311.9 1779.09   323.5 1788.14
   328.3 1790.52   332.1 1791.65   366.9 1795.92   394.8 1799.84   402.6 1801.37
#Mann= 4 ,-1,0
       0      .1       0   294.5    .045       0  305.59      .1       0
     380     .06       0
Bank Sta=294.5,305.59
XS Rating Curve= 0 ,0
Exp/Cntr(USF)=0,0
Exp/Cntr=0.3,0.1

Type RM Length L Ch R = 1 ,6095    ,187.6,184,178.8
XS GIS Cut Line= 3
2211868.55189601702027.5719120292211977.67795859702226.952612826
2211989.16491254  702424.6923202
#Sta/Elev= 30
       0 1806.11    24.6 1799.38    29.2 1798.97    39.2 1796.16    61.1 1791.44
    68.7 1790.35    79.4 1790.24   107.5 1788.63   112.9 1787.24   124.7 1782.52
   129.5 1781.64   142.4 1780.88   147.8 1781.19   161.4 1783.25   190.8 1782.37
   221.9 1778.95   233.5 1775.98   245.5 1774.99   269.6 1775.81   273.6 1775.05
  277.051773.498   281.6 1772.87   285.6 1773.47   293.6 1776.47   309.7 1775.67
   325.7 1776.39   349.7  1782.8   369.8 1786.44   393.8 1789.43   425.4 1795.09
#Mann= 4 ,-1,0
       0      .1       0  277.05    .045       0   285.6      .1       0
  425.36     .06       0
Bank Sta=277.05,285.6
XS Rating Curve= 0 ,0
Exp/Cntr(USF)=0,0
Exp/Cntr=0.3,0.1

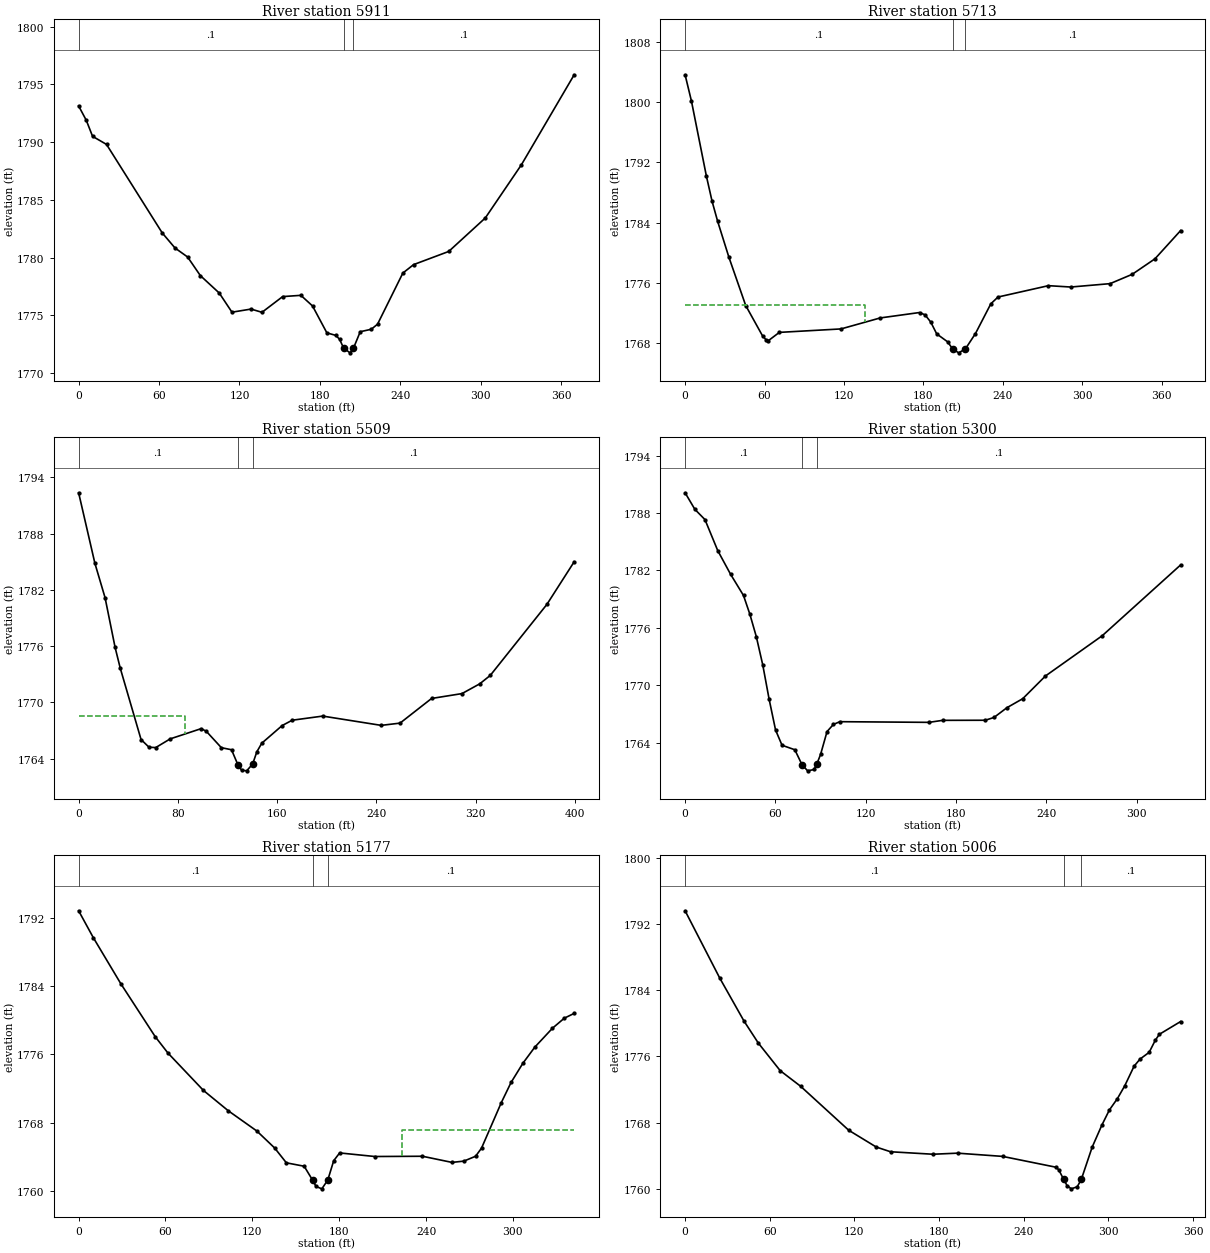
Type RM Length L Ch R = 1 ,5911    ,195.7,198.3,199.2
XS GIS Cut Line= 2
2211716.40650431702164.3335644062211913.12879576702477.361264657
#Sta/Elev= 30
       0 1793.14     5.7  1791.9    10.4 1790.51    20.8 1789.81    62.4 1782.14
    71.9 1780.84    81.3 1780.06    90.8 1778.45   104.9 1776.94   114.4 1775.28
   128.6 1775.55   136.8 1775.27   152.2 1776.63   165.8 1776.74   174.5 1775.82
   185.2 1773.49   191.9 1773.27   194.7 1772.93   197.7 1772.17   202.5 1771.76
  205.051772.164   210.1 1773.59   218.3  1773.8     223 1774.24   241.9 1778.67
   249.9  1779.4   276.1 1780.54   303.4 1783.44   330.3 1788.04   369.7 1795.84
#Mann= 3 ,-1,0
       0      .1       0   197.7    .045       0  205.05      .1       0
Bank Sta=197.7,205.05
XS Rating Curve= 0 ,0
Exp/Cntr(USF)=0,0
Exp/Cntr=0.3,0.1

Type RM Length L Ch R = 1 ,5713    ,202.5,204.2,205.6
XS GIS Cut Line= 2
2211581.37804713702217.9271490042211704.45255379702571.561231487
#Sta/Elev= 30
       0 1803.66     4.8 1800.16    16.1 1790.18    20.4 1786.83    24.6 1784.17
    33.1  1779.4    45.8 1772.98    58.5 1768.95    61.3  1768.4    62.7 1768.28
    71.2 1769.41   117.8 1769.87   147.4 1771.33   177.1 1772.05   181.3 1771.74
   185.6 1770.78   190.1 1769.21   198.3 1768.16   202.1 1767.22   206.7 1766.69
   211.81767.217   219.4 1769.26     231 1773.21   236.4 1774.11   274.5 1775.62
   291.4 1775.44   321.1 1775.89   337.8 1777.13     355 1779.19   374.4 1782.95
#Mann= 3 ,-1,0
       0      .1       0   202.1    .045       0   211.8      .1       0
#XS Ineff= 2 , 0
          135.97 1773.09
Permanent Ineff=
       F       F
Bank Sta=202.1,211.8
XS Rating Curve= 0 ,0
Exp/Cntr(USF)=0,0
Exp/Cntr=0.3,0.1

Type RM Length L Ch R = 1 ,5509    ,217.6,208.4,195.5
XS GIS Cut Line= 3
2211434.50913584702344.2836425132211480.45695166702578.945701887
2211606.81344517702677.405307218
#Sta/Elev= 30
       0 1792.35    13.1 1784.83    21.3 1781.16    29.4 1775.85    33.5 1773.66
    50.3 1766.03    56.7 1765.21    62.1 1765.17    73.8  1766.1    98.7 1767.19
   102.8 1766.92     115 1765.16   123.2 1764.94   128.3 1763.35   131.3 1762.76
   135.4 1762.69  140.221763.417   143.6 1764.72   147.6 1765.64     164 1767.52
   172.1 1768.09   196.7 1768.53   243.8 1767.54     259 1767.78   284.4 1770.41
   308.9 1770.93   323.2 1771.97   331.7 1772.87   377.3 1780.44   399.3 1784.99
#Mann= 3 ,-1,0
       0      .1       0   128.3    .045       0  140.22      .1       0
#XS Ineff= 2 , 0
           85.81 1768.49
Permanent Ineff=
       F       F
Bank Sta=128.3,140.22
XS Rating Curve= 0 ,0
Exp/Cntr(USF)=0,0
Exp/Cntr=0.3,0.1

Type RM Length L Ch R = 1 ,5300    ,125.3,123.9,122.3
XS GIS Cut Line= 2
2211263.84581993702601.099113086 2211572.3525833 702715.96865264
#Sta/Elev= 30
       0 1790.11     6.5 1788.38    13.2 1787.31    21.7 1784.07    30.2 1781.61
    38.8 1779.39      43 1777.45    47.3  1775.1    51.6 1772.14    55.8 1768.58
    60.1 1765.35    64.4 1763.76    72.9 1763.29   77.611761.749    81.4 1761.09
    85.7 1761.23    87.4 1761.76      90  1762.8    94.3 1765.19    98.5 1765.93
   102.8 1766.22     162 1766.15   171.1 1766.36   199.4 1766.37   205.2 1766.66
   213.8 1767.68   224.3 1768.62   239.4 1770.99   277.1 1775.19   329.2 1782.58
#Mann= 3 ,-1,0
       0      .1       0   77.61    .045       0    87.4      .1       0
Bank Sta=77.61,87.4
XS Rating Curve= 0 ,0
Exp/Cntr(USF)=0,0
Exp/Cntr=0.3,0.1

Type RM Length L Ch R = 1 ,5177    ,162.8,170.8,175.8
XS GIS Cut Line= 3
2211214.78011661702652.6837413132211268.11240283702735.553909134
2211506.87694576702784.783711799
#Sta/Elev= 30
       0 1792.84    10.1  1789.7    29.1  1784.3    52.9 1778.08    61.7 1776.16
    86.2 1771.78   103.4 1769.39   123.1 1767.02   135.4 1765.03   143.5 1763.29
   155.8 1762.89  161.611761.258     164 1760.52     168 1760.24   172.1 1761.27
   176.2 1763.54   180.3 1764.45   204.6 1764.03   237.5 1764.06   257.9 1763.34
   266.1 1763.49   274.2 1764.06   278.3 1765.01     292 1770.36   298.7 1772.71
   306.9 1774.97   315.1 1776.85   327.3 1779.07   335.5 1780.25   342.3 1780.81
#Mann= 3 ,-1,0
       0      .1       0  161.61    .045       0   172.1      .1       0
#XS Ineff= 2 , 0
                          223.32         1767.08
Permanent Ineff=
       F       F
Bank Sta=161.61,172.1
XS Rating Curve= 0 ,0
Exp/Cntr(USF)=0,0
Exp/Cntr=0.3,0.1

Type RM Length L Ch R = 1 ,5006    ,305.7,312,314.9
XS GIS Cut Line= 4
2211195.64640513702671.4141164162211278.71532646702783.801480569
2211308.03376928702855.3524422192211398.39087062702954.495251523
#Sta/Elev= 30
       0 1793.64    24.5 1785.51    41.7  1780.3    51.9 1777.62    67.4 1774.28
    81.8  1772.4     116 1767.06   135.5 1765.03   145.6 1764.46   175.7 1764.16
   193.1 1764.29     225  1763.9   262.8 1762.59   264.8 1762.28   268.3 1761.12
   270.7 1760.36   273.7 1759.97   277.9 1760.22   280.8 1761.11   288.5 1765.02
   295.3 1767.66   300.7 1769.52   306.4  1770.9   311.6 1772.45   318.2 1774.82
   322.4 1775.68   328.9  1776.5   333.2 1777.95   336.1 1778.68   351.2 1780.23
#Mann= 3 ,-1,0
       0      .1       0   268.3    .045       0   280.8      .1       0
Bank Sta=268.3,280.8
XS Rating Curve= 0 ,0
Exp/Cntr(USF)=0,0
Exp/Cntr=0.3,0.1

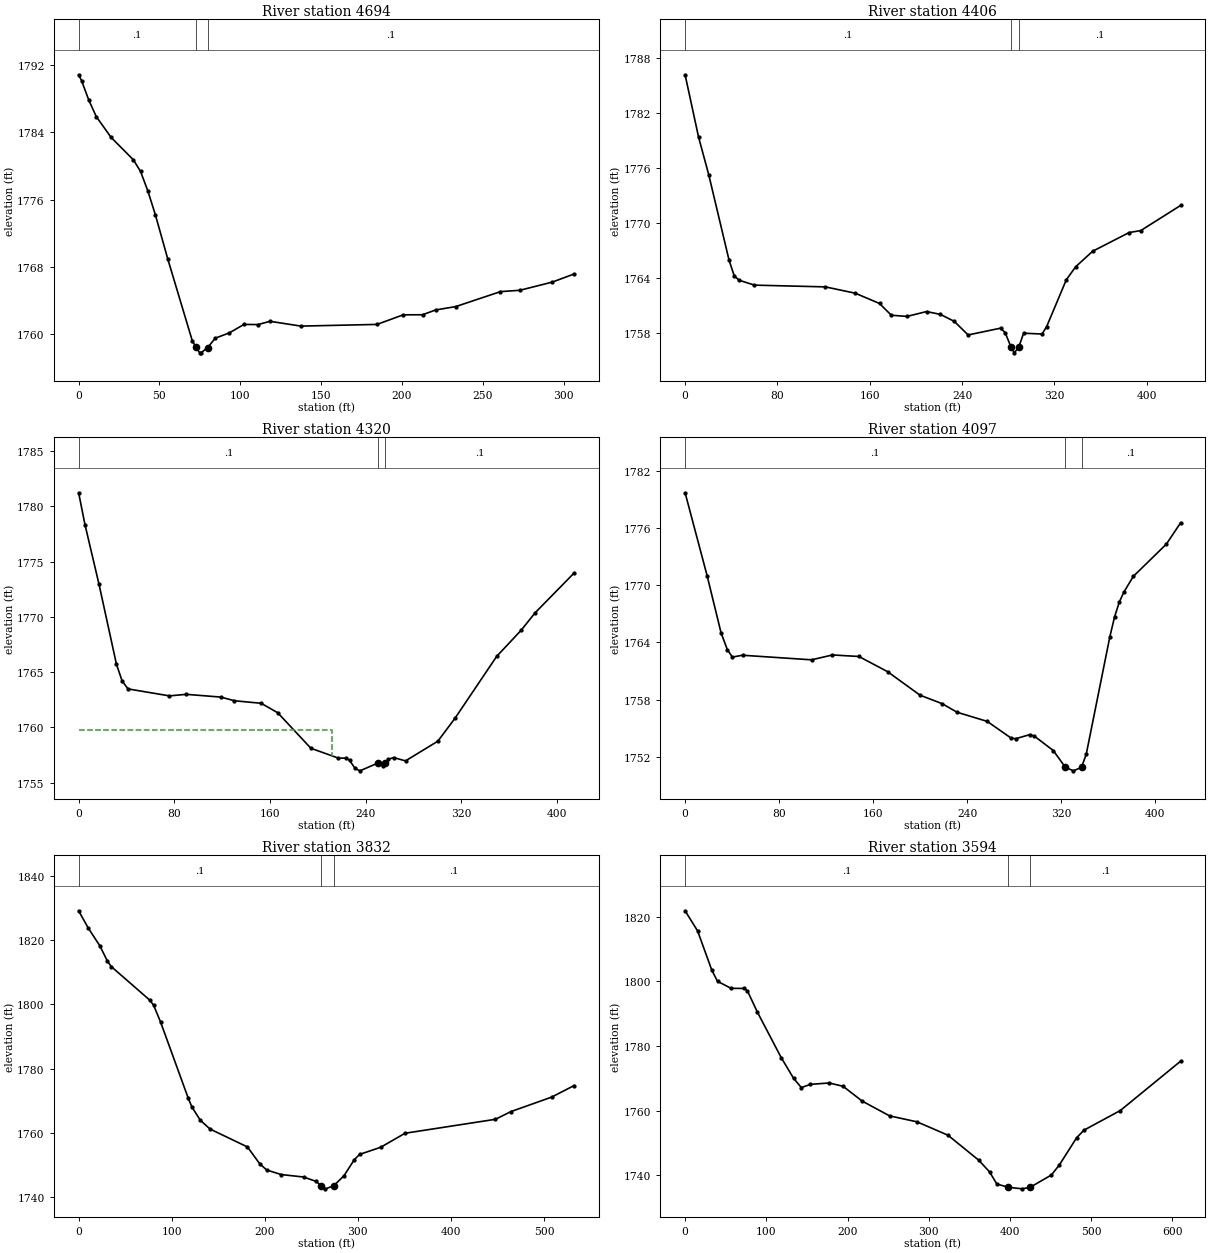
Type RM Length L Ch R = 1 ,4694    ,296.7,287.9,277.1
XS GIS Cut Line= 3
2211038.84100685702803.6305212532211135.93438863702979.121151283
2211241.71824385702971.579126265
#Sta/Elev= 30
       0 1790.85     1.8 1790.16     6.3 1787.83    10.9 1785.88    20.1  1783.4
    33.8 1780.75    38.3 1779.36    42.9 1776.99    47.5 1774.19    55.1 1768.98
    70.3 1759.23    72.61758.427    74.9  1757.8    75.7 1757.78   79.861758.408
    84.5 1759.52    93.2 1760.15   102.3 1761.16     111 1761.14   118.4 1761.53
   137.5 1760.96   184.6 1761.16   200.8  1762.3   212.8 1762.31   220.9 1762.88
   233.3 1763.28     261 1765.06     273 1765.22     293 1766.19   306.6 1767.16
#Mann= 3 ,-1,0
       0      .1       0    72.6    .045       0   79.86      .1       0
Bank Sta=72.6,79.86
XS Rating Curve= 0 ,0
Exp/Cntr(USF)=0,0
Exp/Cntr=0.3,0.1

Type RM Length L Ch R = 1 ,4406    ,81.4,86.1,91.3
XS GIS Cut Line= 6
2210904.96932406702910.4967841022210964.28762809703040.610355425
2210995.08304907703058.0940296262211019.70367969703048.635080997
2211137.50800049703042.3219350972211230.09058524703095.390946752
#Sta/Elev= 30
       0 1786.15    11.7 1779.34    20.5 1775.25    38.1 1765.94    42.5 1764.26
    46.7 1763.76    60.1 1763.22   121.6 1763.03   147.5 1762.34   168.5 1761.22
   178.7 1759.94   192.3 1759.81   209.3 1760.34   221.3 1760.03   233.3 1759.27
   245.3 1757.79   273.4 1758.53   277.4 1758.04   282.41756.498   285.4 1755.84
   289.4 1756.53   293.4 1757.98   309.4 1757.89   313.4 1758.71   330.4  1763.8
   338.5 1765.22   353.2 1766.91   384.8 1768.95     395 1769.17   429.5 1771.91
#Mann= 3 ,-1,0
       0      .1       0   282.4    .045       0   289.4      .1       0
Bank Sta=282.4,289.4
XS Rating Curve= 0 ,0
Exp/Cntr(USF)=0,0
Exp/Cntr=0.3,0.1

Type RM Length L Ch R = 1 ,4320    ,208.4,223,234.2
XS GIS Cut Line= 3
2210877.14686869702931.1743555532210962.74100354 703055.52809864
2211190.99202981703186.880104325
#Sta/Elev= 30
       0 1781.23     5.3 1778.35      17 1772.97    31.6 1765.73    36.4  1764.2
    41.3 1763.49    75.9 1762.86      90    1763     119 1762.75   130.2 1762.42
   152.6 1762.19   166.5 1761.33   194.2 1758.12   217.2 1757.23   223.5 1757.23
   226.5 1757.03   231.1  1756.3   235.2 1756.08   250.5  1756.8   254.1 1756.54
  256.431756.802   258.8 1757.12   263.4 1757.28   273.3 1756.98   300.3 1758.76
   314.7 1760.84   349.5 1766.43     370  1768.8   381.7 1770.38   414.3 1773.98
#Mann= 3 ,-1,0
       0      .1       0   250.5    .045       0  256.43      .1       0
#XS Ineff= 2 , 0
          211.77 1759.74
Permanent Ineff=
       F       F
Bank Sta=250.5,256.43
XS Rating Curve= 0 ,0
Exp/Cntr(USF)=0,0
Exp/Cntr=0.3,0.1

Type RM Length L Ch R = 1 ,4097    ,270.3,265,256.7
XS GIS Cut Line= 3
2210841.75014827702951.7969660382210922.83163326703155.165280851
2210905.55197253703357.204390992
#Sta/Elev= 30
       0 1779.68    18.7 1771.01    30.6 1765.01    35.9 1763.26    40.2 1762.47
    48.9 1762.66   107.6 1762.18   125.4 1762.69   147.9 1762.53   172.3 1760.94
     200 1758.47   218.9 1757.58   231.4 1756.69   257.1 1755.73   277.2    1754
   281.2 1753.91   293.2 1754.34   297.2 1754.19   313.3 1752.68   323.6 1750.92
   330.5 1750.55   337.4 1750.93   341.4 1752.31   361.5 1764.62   365.5 1766.69
   369.5 1768.23   373.5  1769.3   381.5 1770.93   409.6 1774.31   421.7 1776.54
#Mann= 3 ,-1,0
       0      .1       0   323.6    .045       0   337.4      .1       0
Bank Sta=323.6,337.4
XS Rating Curve= 0 ,0
Exp/Cntr(USF)=0,0
Exp/Cntr=0.3,0.1

Type RM Length L Ch R = 1 ,3832    ,240.9,237.7,234.4
XS GIS Cut Line= 5
2210619.54910413702907.1166656912210650.56387981 703031.17576841
2210717.02411341703094.6822138492210765.02317101703175.172941207
2210853.63681581703375.292089044
#Sta/Elev= 30
       0  1829.2    10.4 1823.78    22.7 1818.32      31 1813.45    35.1 1811.79
    76.3 1801.36    80.5 1799.77      88 1794.53   117.7  1770.8   121.7 1767.99
   130.8 1763.84   141.2 1761.12   181.4 1755.53   194.5 1750.31     202 1748.35
   217.6 1746.93   241.6 1746.16   255.3 1744.78   260.61743.367     265 1742.47
   273.9 1743.36   285.2  1746.6   296.2 1751.57   301.9 1753.21   324.5 1755.43
   350.7 1759.81   447.8 1764.16   464.4 1766.56   508.2 1771.08   532.4  1774.7
#Mann= 3 ,-1,0
       0      .1       0   260.6    .045       0   273.9      .1       0
Bank Sta=260.6,273.9
XS Rating Curve= 0 ,0
Exp/Cntr(USF)=0,0
Exp/Cntr=0.3,0.1

Type RM Length L Ch R = 1 ,3594    ,172.9,183.1,186.1
XS GIS Cut Line= 4
 2210414.0512008702957.3400684892210391.14504858 703098.63860622
2210538.24412664703203.2429328062210666.25061766703459.637575231
#Sta/Elev= 30
       0 1821.88    15.4 1815.64    32.9 1803.49    39.9 1800.06    56.6 1797.88
    72.8 1797.85    76.8 1797.08      89 1790.53   118.4 1776.42   133.6 1770.04
   143.1 1767.18   154.3 1768.16   177.3  1768.6   194.5 1767.58     218    1763
   251.8 1758.42   285.6 1756.57   323.6 1752.45   361.6  1744.7     375 1741.05
   383.9 1737.32   398.1 1736.33   415.2 1735.84   424.9 1736.33     451 1740.11
   460.7 1743.18   482.3  1751.7   491.2    1754   535.9 1760.07   610.2 1775.35
#Mann= 3 ,-1,0
       0      .1       0   398.1    .045       0   424.9      .1       0
Bank Sta=398.1,424.9
XS Rating Curve= 0 ,0
Exp/Cntr(USF)=0,0
Exp/Cntr=0.3,0.1

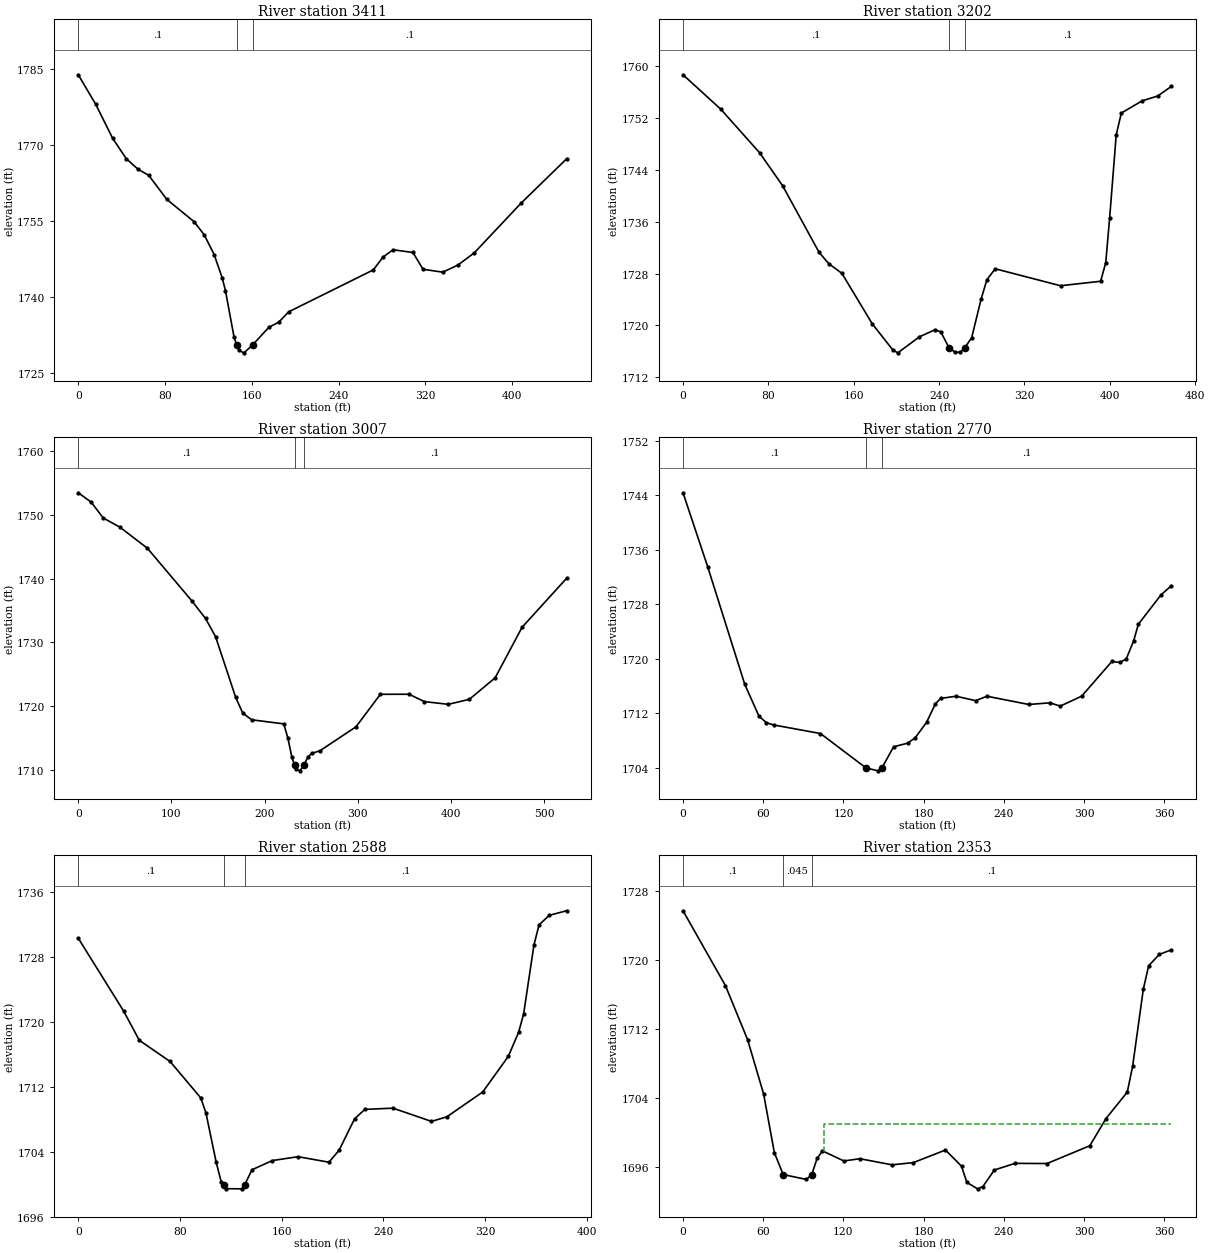
Type RM Length L Ch R = 1 ,3411    ,208.3,208.8,207
XS GIS Cut Line= 3
2210370.70066753703050.7151888862210398.96222092703149.174794218
2210568.53154121703452.758577326
#Sta/Elev= 30
       0 1783.87    16.1 1778.05    31.7 1771.34    44.2 1767.34    54.9 1765.28
      65 1764.03    81.6 1759.31     107 1754.86   116.2 1752.28   125.3 1748.41
   132.7 1743.83   135.7 1741.32   143.7 1732.06  146.22 1730.54   148.3  1729.5
   152.8 1729.03  160.871730.607   175.7 1734.06   184.9 1735.08   194.1 1737.13
     272 1745.38   281.1 1747.93   290.3 1749.36   308.6 1748.82   317.9 1745.51
   336.1 1744.94   349.9 1746.32     365 1748.72   408.4 1758.57   450.2 1767.28
#Mann= 3 ,-1,0
       0      .1       0  146.22    .045       0  160.87      .1       0
Bank Sta=146.22,160.87
XS Rating Curve= 0 ,0
Exp/Cntr(USF)=0,0
Exp/Cntr=0.3,0.1

Type RM Length L Ch R = 1 ,3202    ,187.7,194.7,196
XS GIS Cut Line= 3
 2210192.4167496703106.7252822422210253.49817142703256.238016264
 2210422.1558287703499.652040556
#Sta/Elev= 30
       0  1758.6    35.4  1753.3    71.8 1746.59    93.4  1741.5   127.5 1731.27
   136.6 1729.52   148.9 1728.03   177.3 1720.27   196.7 1716.22   201.3 1715.79
   221.6 1718.26   236.4 1719.36   241.7 1718.99  249.291716.577   255.1 1715.88
     260 1715.88     2641716.576   270.5  1718.1   279.4 1724.07   284.8 1727.05
   292.6 1728.73   353.8 1726.12   391.4 1726.81   396.2 1729.68   399.8 1736.48
     406 1749.33   410.8 1752.71   430.3 1754.59   444.9 1755.33   457.6  1756.8
#Mann= 3 ,-1,0
       0      .1       0  249.29    .045       0     264      .1       0
Bank Sta=249.29,264
XS Rating Curve= 0 ,0
Exp/Cntr(USF)=0,0
Exp/Cntr=0.3,0.1

Type RM Length L Ch R = 1 ,3007    ,241.5,237.6,232.5
XS GIS Cut Line= 2
2210055.66729775703132.2518465872210249.85151937703619.079895172
#Sta/Elev= 30
       0 1753.42    13.9 1751.95    26.8 1749.47    44.6 1748.05    74.2 1744.74
   121.6 1736.56   136.6 1733.75   147.4 1730.89     169 1721.39   176.6 1718.93
   186.2 1717.89   220.6 1717.25   224.9 1715.09   229.2  1712.1  232.191710.763
   233.5 1710.23   237.9  1709.9   242.2 1710.79   246.5 1712.08   250.8 1712.64
   259.4 1713.04   298.1 1716.79   324.3 1721.88   355.1 1721.89   371.4 1720.74
   397.2 1720.31   419.8 1721.09   447.5 1724.46   476.4 1732.37   524.1 1740.02
#Mann= 3 ,-1,0
       0      .1       0  232.19    .045       0   242.2      .1       0
Bank Sta=232.19,242.2
XS Rating Curve= 0 ,0
Exp/Cntr(USF)=0,0
Exp/Cntr=0.3,0.1

Type RM Length L Ch R = 1 ,2770    ,190.8,182.2,174.7
XS GIS Cut Line= 2
2209862.79654616703405.1981249292210128.63748056703655.449621814
#Sta/Elev= 30
       0 1744.38    18.4 1733.54    46.2 1716.22    56.8 1711.56    62.3 1710.61
    67.8 1710.27   102.8 1709.01   136.8 1703.96   145.9 1703.53  148.751703.972
   157.5 1707.07   167.9 1707.59   173.6 1708.38   182.1 1710.65   188.7 1713.37
   192.6 1714.17   204.2 1714.49   218.8 1713.84   227.3 1714.49   258.5 1713.28
   274.3 1713.52   282.1 1713.04   298.1  1714.5   320.7  1719.6   326.8 1719.45
   331.5 1719.99     337 1722.65   340.5 1725.07   357.5  1729.4   365.1 1730.71
#Mann= 3 ,-1,0
       0      .1       0   136.8    .045       0  148.75      .1       0
Bank Sta=136.8,148.75
XS Rating Curve= 0 ,0
Exp/Cntr(USF)=0,0
Exp/Cntr=0.3,0.1

Type RM Length L Ch R = 1 ,2588    ,212.2,234.7,249.3
XS GIS Cut Line= 2
2209744.55385346703629.1937270592210125.62899262703675.688540688
#Sta/Elev= 30
       0 1730.29    35.6 1721.33      48 1717.71    72.2  1715.1    96.3 1710.62
   100.4 1708.76   108.4 1702.72   112.4 1700.26   114.3 1699.87   116.5 1699.43
   128.6 1699.41  130.711699.866   136.6 1701.76   152.7  1702.9   172.9 1703.37
   197.1 1702.69   205.1 1704.17   217.2 1708.02   225.3  1709.2   247.5 1709.35
   277.7 1707.72   289.8 1708.28     318 1711.34   338.1 1715.72   346.2 1718.68
   350.2 1720.98   358.3 1729.46   362.3 1731.93   370.3 1733.11   383.9 1733.67
#Mann= 3 ,-1,0
       0      .1       0   114.3    .045       0  130.71      .1       0
Bank Sta=114.3,130.71
XS Rating Curve= 0 ,0
Exp/Cntr(USF)=0,0
Exp/Cntr=0.3,0.1

Type RM Length L Ch R = 1 ,2353    ,252.5,242.5,233
XS GIS Cut Line= 2
2209742.91286004703656.9082826342209750.29733044704022.029319073
#Sta/Elev= 30
       0 1725.72    31.7 1717.03    48.3 1710.75    60.3 1704.42    68.3 1697.63
    74.91695.073    92.3  1694.5    96.3 1695.07   100.3 1696.95   104.3 1697.82
   120.3 1696.65   132.3 1696.91   156.3  1696.2   172.3 1696.46   196.3 1697.92
   208.3 1696.04   212.3 1694.16   220.3 1693.41   224.3 1693.68   232.9  1695.6
   248.3 1696.37   272.3 1696.35   304.3 1698.42   316.3 1701.56   332.3 1704.65
   336.3 1707.65   344.3 1716.61   348.3 1719.34   356.3 1720.65   365.2 1721.18
#Mann= 3 ,-1,0
       0      .1       0    74.9    .045       0    96.3      .1       0
#XS Ineff= 2 , 0
                          105.29         1700.91
Permanent Ineff=
       F       F
Bank Sta=74.9,96.3
XS Rating Curve= 0 ,0
Exp/Cntr(USF)=0,0
Exp/Cntr=0.3,0.1

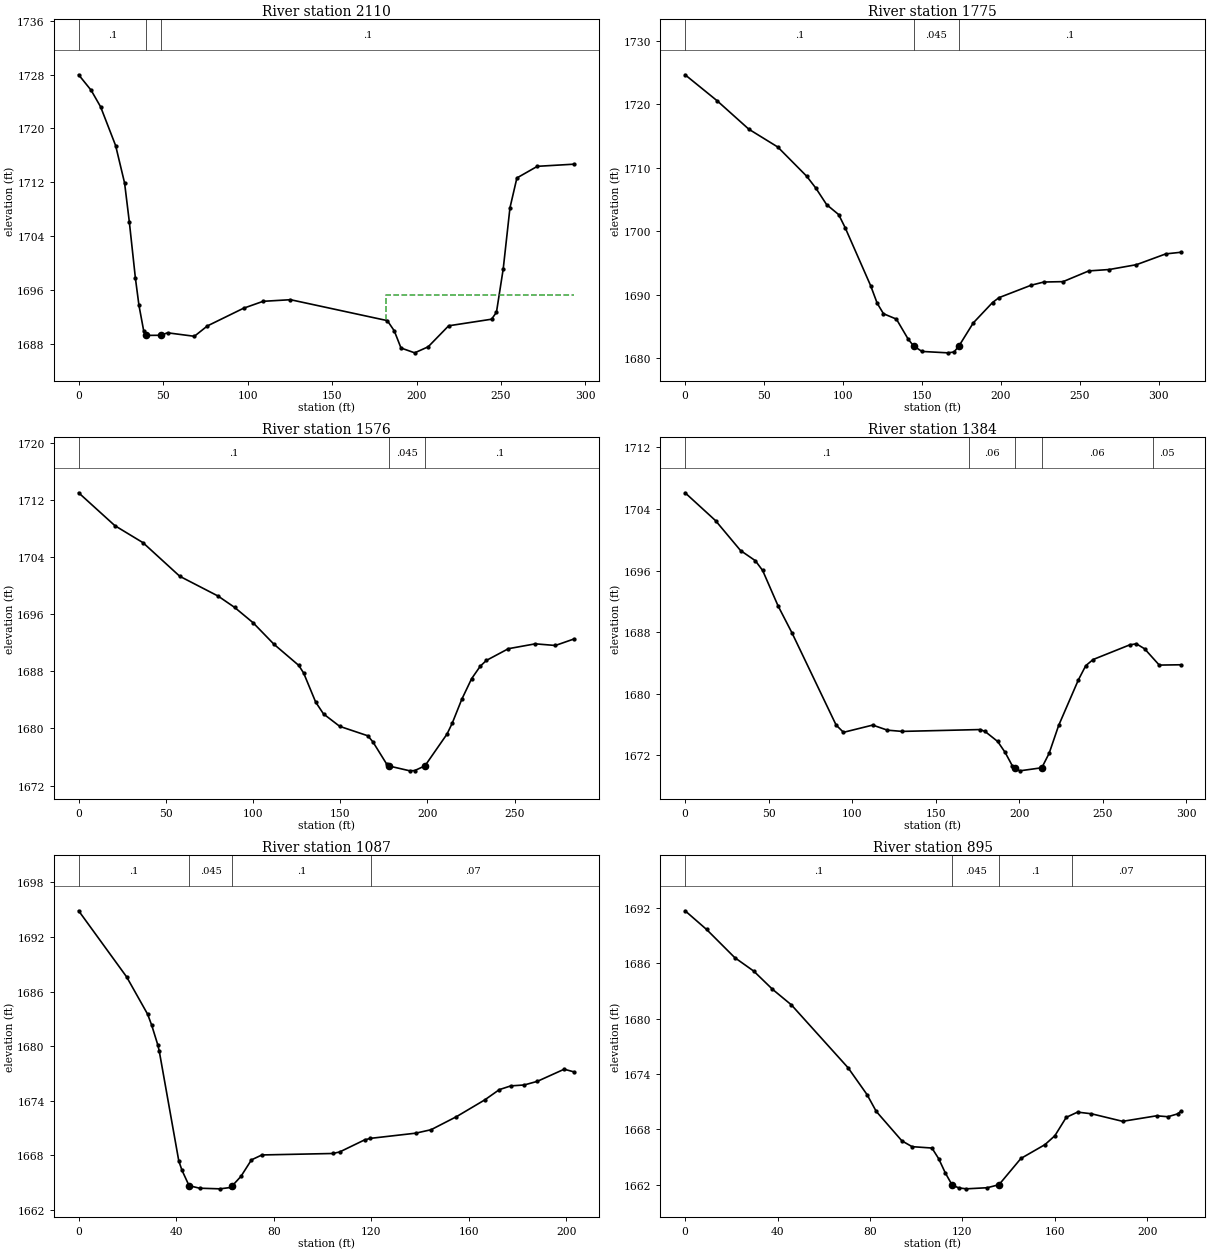
Type RM Length L Ch R = 1 ,2110    ,317.3,335.6,344.5
XS GIS Cut Line= 3
 2209488.8266259703794.1115650842209579.90176083703880.263719749
2209601.23467532704046.824552102
#Sta/Elev= 30
       0 1727.96     7.4 1725.66      13  1723.2    21.9 1717.43    27.2 1711.87
      30  1706.1    33.6 1697.72    35.7 1693.69    38.5  1689.9   40.091689.214
    48.7 1689.23    52.6  1689.6    68.5 1689.08    76.2 1690.62    97.6 1693.25
   109.2 1694.28   125.4 1694.52   182.7 1691.41   186.8  1689.9   190.8 1687.34
   198.9 1686.62   206.9 1687.52     219 1690.64   244.4 1691.62   247.3 1692.65
   251.3 1699.09   255.3 1708.19   259.4 1712.62   271.5 1714.35   293.3 1714.67
#Mann= 3 ,-1,0
       0      .1       0   40.09    .045       0    48.7      .1       0
#XS Ineff= 2 , 0
                          181.85         1695.26
Permanent Ineff=
       F       F
Bank Sta=40.09,48.7
XS Rating Curve= 0 ,0
Exp/Cntr(USF)=0,0
Exp/Cntr=0.3,0.1

Type RM Length L Ch R = 1 ,1775    ,213.2,198.3,188
XS GIS Cut Line= 2
2209291.76560099703917.4291818852209347.37704474704226.482943066
#Sta/Elev= 30
       0 1724.66    20.1 1720.61    40.4 1716.09    58.7 1713.29      77  1708.7
    82.8 1706.83    89.7 1704.21    97.3 1702.65   101.4  1700.6   117.6 1691.44
   121.7  1688.7   125.7 1687.04   133.9 1686.19   141.4 1683.02   144.8 1681.96
   150.1  1681.1   166.4 1680.88   170.4 1681.01  173.541681.965   182.6 1685.59
   194.8  1688.8   198.9 1689.57   219.2 1691.52   227.3 1692.03   239.5 1692.09
   255.8 1693.78   268.8    1694     286 1694.76   304.6 1696.46     314 1696.71
#Mann= 3 ,-1,0
       0      .1       0   144.8    .045       0  173.54      .1       0
Bank Sta=144.8,173.54
XS Rating Curve= 0 ,0
Exp/Cntr(USF)=0,0
Exp/Cntr=0.3,0.1

Type RM Length L Ch R = 1 ,1576    ,186.4,192.3,197.9
XS GIS Cut Line= 2
2209044.70492465704082.4401871172209256.21074351704272.066093682
#Sta/Elev= 30
       0 1713.01    20.8  1708.4    36.9 1706.02      58 1701.31    79.9 1698.55
    89.4 1696.96     100 1694.81     112 1691.79   126.2 1688.83     129 1687.76
   135.9 1683.69   140.4 1682.03   149.7 1680.29   165.8 1678.97   168.7 1678.12
   176.6 1675.01   177.9 1674.74   189.9 1674.06   192.7  1674.1  198.561674.761
   211.2 1679.21   214.2 1680.74   219.7  1684.1   225.3 1686.97   230.3 1688.73
   233.8 1689.53   246.4 1691.17   261.8 1691.85   273.3 1691.62   284.1 1692.54
#Mann= 3 ,-1,0
       0      .1       0   177.9    .045       0  198.56      .1       0
Bank Sta=177.9,198.56
XS Rating Curve= 0 ,0
Exp/Cntr(USF)=0,0
Exp/Cntr=0.3,0.1

Type RM Length L Ch R = 1 ,1384    ,294.6,296.8,295.3
XS GIS Cut Line= 2
 2208952.6269604704138.9632938822209075.70146707704408.815545532
#Sta/Elev= 30
       0  1706.1    18.2 1702.49    33.2  1698.6      42 1697.29    46.4 1696.02
    55.7 1691.39      64  1687.9    90.4 1675.94    94.8    1675   112.3 1675.94
   121.1 1675.28   129.9 1675.12   176.5 1675.36   179.5 1675.12   187.1 1673.81
   191.5 1672.41   195.9 1670.64  197.321670.398   200.3    1670   213.5  1670.4
   217.9 1672.28   223.6  1675.9   235.4 1681.81   239.8 1683.65   244.2 1684.45
   266.2 1686.36   270.1 1686.49     275 1685.85   283.8 1683.73   296.6 1683.77
#Mann= 5 ,-1,0
       0      .1       0     170     .06       0  197.32    .045       0
   213.5     .06       0     280     .05       0
Bank Sta=197.32,213.5
XS Rating Curve= 0 ,0
Exp/Cntr(USF)=0,0
Exp/Cntr=0.3,0.1

Type RM Length L Ch R = 1 ,1087    ,195.3,192.5,188.3
XS GIS Cut Line= 3
2208740.20947853 704286.65270188  2208774.852673 704380.55399215
2208845.05072495704456.222022174
#Sta/Elev= 30
       0 1694.86    19.7  1687.6    28.3 1683.51      30 1682.28    32.5 1680.12
    33.1 1679.42    41.1 1667.39    42.4 1666.38    45.3 1664.69    49.6 1664.41
      58 1664.34    62.4 1664.49   63.081664.688    66.6 1665.71    70.9 1667.52
    75.2 1668.06   104.3 1668.22   107.1 1668.39   117.3 1669.71   119.7 1669.88
   138.3 1670.45   144.6 1670.83     155 1672.26   166.6  1674.1   172.6 1675.23
   177.3 1675.64   182.8 1675.74   188.2 1676.14   199.2 1677.47   203.3 1677.17
#Mann= 4 ,-1,0
       0      .1       0    45.3    .045       0   63.08      .1       0
  120.09     .07       0
Bank Sta=45.3,63.08
XS Rating Curve= 0 ,0
Exp/Cntr(USF)=0,0
Exp/Cntr=0.3,0.1

Type RM Length L Ch R = 1 ,895     ,116.9,118.2,120.2
XS GIS Cut Line= 3
2208575.19847329704344.0874716572208592.52007053704429.783794816
2208665.45311152704533.713378222
#Sta/Elev= 30
       0 1691.72     9.3 1689.69    21.5 1686.63    29.7 1685.17    37.8  1683.2
      46  1681.5    70.5 1674.68    78.7 1671.77    82.7 1669.94    93.8 1666.74
    98.2 1666.11   106.8 1665.96   109.7 1664.81   112.6 1663.25   115.5 1661.96
   118.3 1661.64   121.6 1661.53   130.7 1661.65  135.811661.981   145.3 1664.83
   155.7 1666.33     160  1667.3   164.9 1669.29   169.8 1669.86   175.8 1669.68
   189.3 1668.86     204 1669.46   208.9 1669.36   213.1 1669.67   214.4 1669.93
#Mann= 4 ,-1,0
       0      .1       0   115.5    .045       0  135.81      .1       0
  167.43     .07       0
Bank Sta=115.5,135.81
XS Rating Curve= 0 ,0
Exp/Cntr(USF)=0,0
Exp/Cntr=0.3,0.1