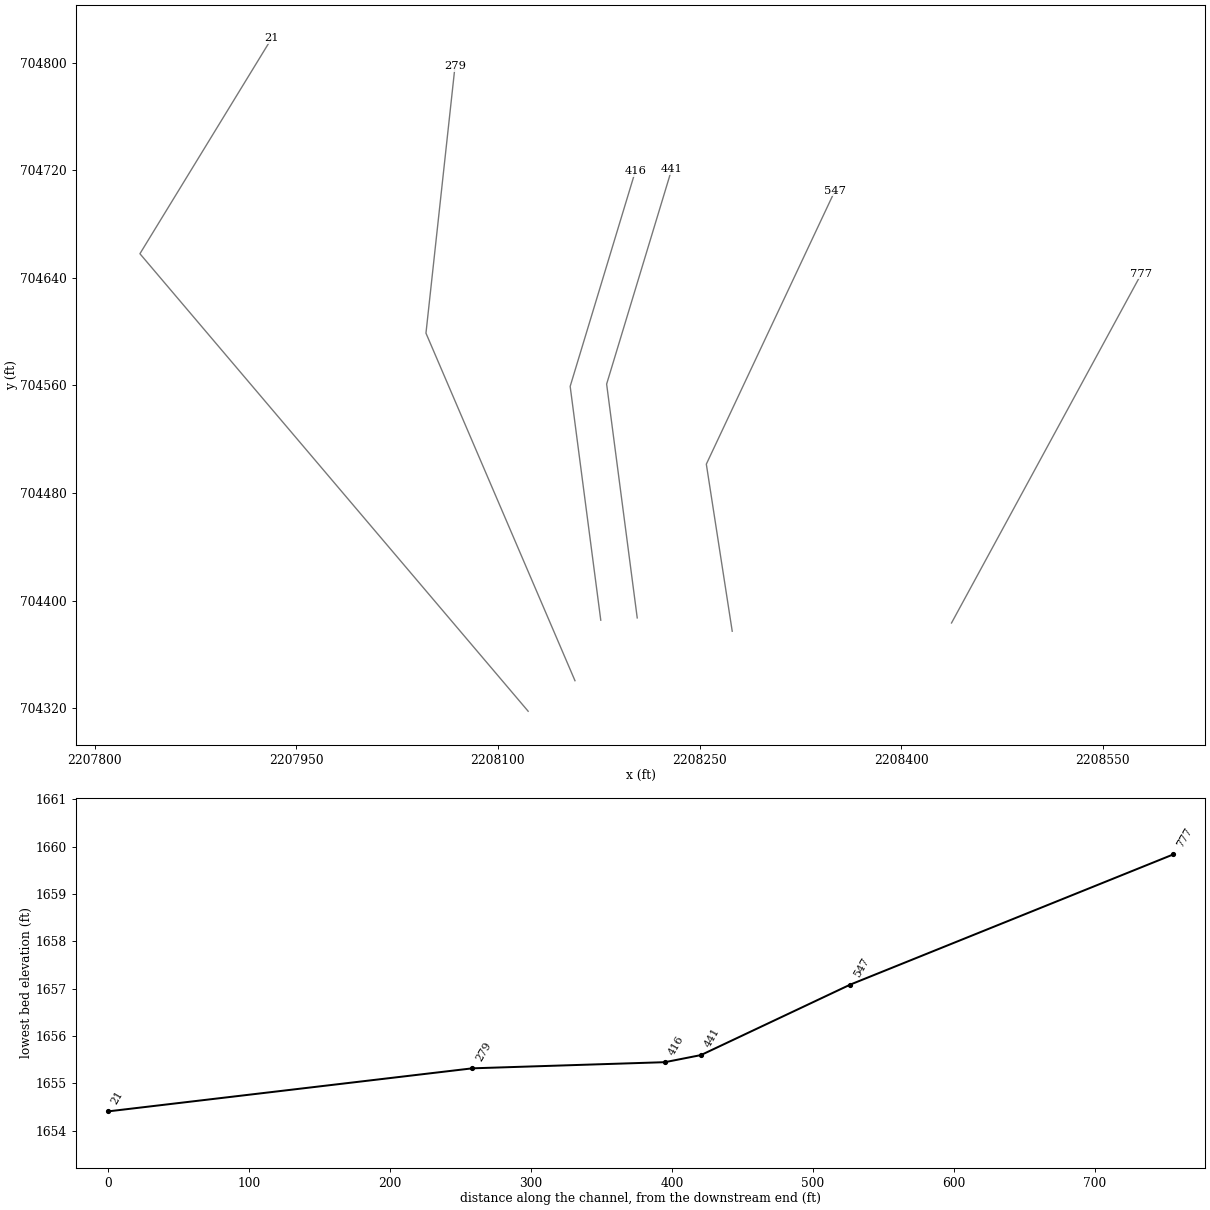
HEC-RAS study SANDRNT1.prj: SANDRNT1

--- SANDRNT1.g01 (geometry) --- (continued)

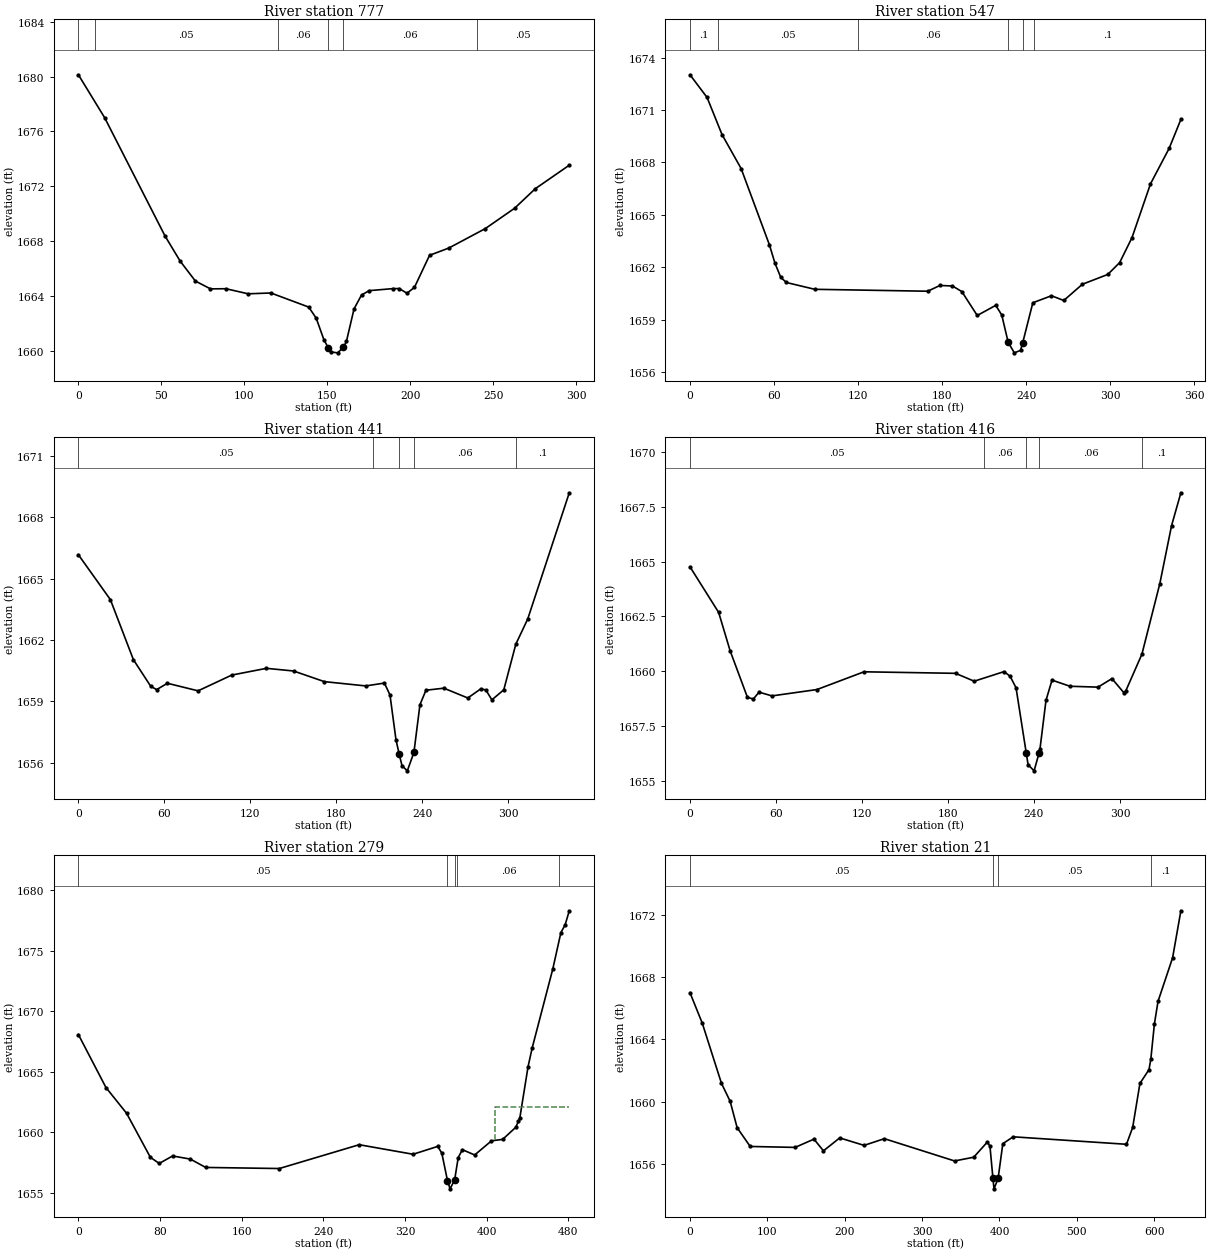
Type RM Length L Ch R = 1 ,777     ,228.3,229.1,229.2
XS GIS Cut Line= 2
2208437.53735843704383.2889811872208578.84512534704643.112939702
#Sta/Elev= 30
       0 1680.14    15.8 1677.01    52.2 1668.37    61.3 1666.54    70.5 1665.08
    79.6 1664.51    88.9 1664.52   102.3 1664.15     116 1664.21   138.8 1663.18
   143.3 1662.37   147.9 1660.81  150.461660.227   152.4  1659.9   156.2 1659.84
   159.7 1660.24   161.5 1660.67   166.1 1663.05   170.6 1664.06   175.2 1664.38
   189.7 1664.53   193.4 1664.53     198 1664.19   202.5 1664.62   211.6 1666.96
   223.2 1667.49   245.2 1668.91   262.9  1670.4   275.3 1671.82   295.8 1673.54
#Mann= 6 ,-1,0
       0      .1       0      10     .05       0     120     .06       0
  150.46    .045       0   159.7     .06       0     240     .05       0
Bank Sta=150.46,159.7
XS Rating Curve= 0 ,0
Exp/Cntr(USF)=0,0
Exp/Cntr=0.3,0.1

Type RM Length L Ch R = 1 ,547     ,104.7,106,107.7
XS GIS Cut Line= 3
2208274.34967922704377.1589590922208255.07621148704501.439595922
2208350.77894786704704.807910735
#Sta/Elev= 30
       0 1673.02    12.2 1671.72    22.9 1669.59    36.5 1667.65    56.7 1663.28
    60.7 1662.22    64.8 1661.42    68.8 1661.12    89.1 1660.73   169.7 1660.62
   178.5 1660.95   187.4 1660.92   194.1  1660.6   205.1 1659.23   218.3 1659.81
   222.6 1659.26   227.2 1657.69   231.6 1657.09     236 1657.23   237.6 1657.68
   244.8 1659.96   258.1 1660.36   266.9 1660.09   280.2 1661.02   298.3 1661.58
   306.8 1662.26   315.6 1663.69   328.8 1666.77   342.1  1668.8   350.5 1670.46
#Mann= 6 ,-1,0
       0      .1       0      20     .05       0     120     .06       0
   227.2    .045       0   237.6     .06       0  245.77      .1       0
Bank Sta=227.2,237.6
XS Rating Curve= 0 ,0
Exp/Cntr(USF)=0,0
Exp/Cntr=0.3,0.1

Type RM Length L Ch R = 1 ,441     ,25.5,25.5,25.5
XS GIS Cut Line= 3
2208203.65858716704387.0681799222208180.88731732704561.001921876
2208229.33682761704720.885305845
#Sta/Elev= 30
       0 1666.16    22.3 1663.97    38.4 1661.03    50.5 1659.73    54.6 1659.57
    62.1 1659.88    83.5 1659.51     107 1660.28   131.2 1660.61   150.1 1660.48
   171.6 1659.96   200.5 1659.75   213.5 1659.89   217.4 1659.31   221.6 1657.11
  223.741656.442   225.8 1655.85   229.5  1655.6   234.1  1656.5   238.3 1658.83
   242.5 1659.54     255 1659.64   271.7 1659.16   280.8 1659.61   284.3 1659.55
   288.5 1659.07   296.8 1659.56   305.2 1661.79   313.5 1663.02   342.5 1669.19
#Mann= 5 ,-1,0
       0     .05       0  205.42     .06       0  223.74    .045       0
   234.1     .06       0  305.42      .1       0
Bank Sta=223.74,234.1
XS Rating Curve= 0 ,0
Exp/Cntr(USF)=0,0
Exp/Cntr=0.3,0.1

Type RM Length L Ch R = 1 ,416     ,135.2,136.6,137.7
XS GIS Cut Line= 3
2208176.52686139704385.3724470612208153.75559155704559.306189016
2208202.20510185704719.189572985
#Sta/Elev= 30
       0 1664.76      20 1662.68      28 1660.93    40.1  1658.8    44.2 1658.73
    48.2 1659.04    57.2 1658.87    88.6 1659.16   121.4 1659.97   185.3  1659.9
   198.3 1659.54   219.2 1659.98   223.4 1659.76   227.5 1659.24   234.6 1656.27
   235.9 1655.73   240.1 1655.45  243.511656.255   244.2 1656.45   248.4 1658.67
   252.6 1659.59   265.1 1659.31   284.7 1659.27   294.4 1659.66   302.8 1659.01
     304 1659.09   315.3 1660.77   327.8 1663.99     336 1666.64   342.5 1668.14
#Mann= 5 ,-1,0
       0     .05       0  205.42     .06       0   234.6    .045       0
  243.51     .06       0  315.42      .1       0
Bank Sta=234.6,243.51
XS Rating Curve= 0 ,0
Exp/Cntr(USF)=0,0
Exp/Cntr=0.3,0.1

Type RM Length L Ch R = 1 ,279     ,257.7,258.5,257.7
XS GIS Cut Line= 3
2208157.33486848704340.3532793712208046.44410878704598.888208524
2208068.05977254704797.345810794
#Sta/Elev= 30
       0 1668.08      27  1663.7    47.2 1661.57    70.5 1657.93    79.2 1657.42
    92.3 1658.04   109.7 1657.78   124.7 1657.09   196.8    1657   275.1 1658.97
   327.9 1658.18     352 1658.83     356 1658.28361.56831656.006   364.1 1655.32
368.57821656.052   372.1 1657.91   376.2 1658.56   388.2 1658.12   404.7 1659.29
   415.6 1659.41   428.5 1660.41     431  1660.9   432.5 1661.21   440.5 1665.42
   444.6 1666.99   464.7 1673.49   472.7 1676.52   476.8 1677.15   480.9 1678.32
#Mann= 5 ,-1,0
       0     .05       0361.5683    .045       0368.5782     .05       0
  371.31     .06       0  471.31      .1       0
#XS Ineff= 2 , 0
                          407.86         1662.12
Permanent Ineff=
       F       F
Bank Sta=361.5683,368.5782
XS Rating Curve= 0 ,0
Exp/Cntr(USF)=0,0
Exp/Cntr=0.3,0.1

Type RM Length L Ch R = 1 ,21      ,,,
XS GIS Cut Line= 3
2208122.49070386704317.6358446762207833.58806841704657.978700937
 2207931.6833732704818.280784378
#Sta/Elev= 30
       0    1667    15.9 1665.04    40.7 1661.18    51.9 1660.03    60.9 1658.34
    77.8 1657.13   135.8 1657.07   160.2  1657.6   172.5 1656.85   193.5 1657.68
     225  1657.2   251.2 1657.63   341.9  1656.2   366.7 1656.44   384.4 1657.42
   387.7 1657.13   391.51655.098   392.9 1654.41   398.2 1655.08   404.3 1657.31
   417.7 1657.75   564.1 1657.27   572.1 1658.35   581.5 1661.18   593.2 1662.06
   595.6 1662.75   600.2    1665   604.9 1666.45   623.7 1669.24   634.4 1672.26
#Mann= 4 ,-1,0
       0     .05       0   391.5    .045       0   398.2     .05       0
  596.43      .1       0
Bank Sta=391.5,398.2
XS Rating Curve= 0 ,0
Exp/Cntr(USF)=0,0
Exp/Cntr=0.3,0.1
LCMann Table=0

Chan Stop Cuts=-1
Use User Specified Reach Order=0
Composite Channel Slope=5